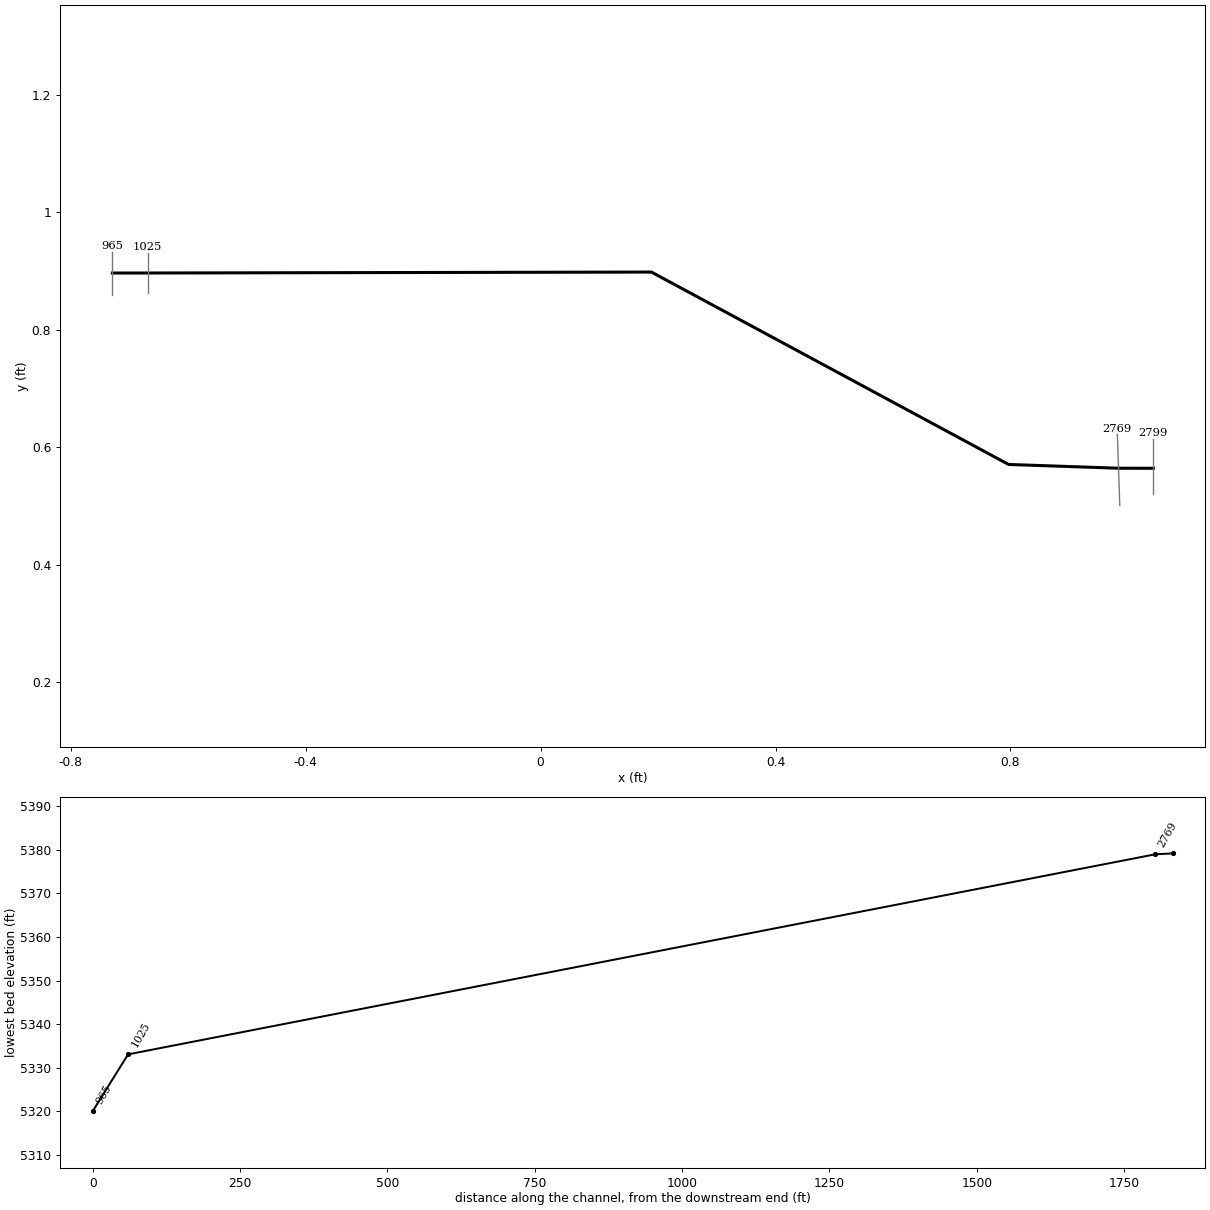
--- NorthArroyodeDom.prj (project) ---

Proj Title=NorthArroyodeDom
Current Plan=p03
Default Exp/Contr=0.3,0.1
English Units
Geom File=g01
Geom File=g02
Flow File=f01
Flow File=f02
Flow File=f03
Flow File=f04
Flow File=f05
Flow File=f06
Flow File=f07
Flow File=f08
Flow File=f09
Flow File=f10
Flow File=f11
Flow File=f12
Plan File=p01
Plan File=p02
Plan File=p03
Y Axis Title=Elevation
X Axis Title(PF)=Main Channel Distance
X Axis Title(XS)=Station
BEGIN DESCRIPTION:
END DESCRIPTION:
DSS Export Rating Curves= 0
DSS Export Rating Curve Sorted= 0
DSS Export Volume Flow Curves= 0
DXF Filename=..\..\NDB_2.
DXF OffsetX= 0
DXF OffsetY= 0
DXF ScaleX= 1
DXF ScaleY= 10

--- NorthArroyodeDom.p03 (plan) ---

Plan Title=Plan 03
Program Version=6.50
Short Identifier=Plan 03
Geom File=g02
Flow File=f12
Subcritical Flow
K Sum by GR= 0
Std Step Tol= 0.01
Critical Tol= 0.01
Num of Std Step Trials= 20
Max Error Tol= 0.3
Flow Tol Ratio= 0.001
Split Flow NTrial= 30
Split Flow Tol= 0.02
Split Flow Ratio= 0.02
Log Output Level= 0
Friction Slope Method= 1
Unsteady Friction Slope Method= 2
Unsteady Bridges Friction Slope Method= 1
Parabolic Critical Depth
Global Vel Dist= 0 , 0 , 0
Global Log Level= 0
CheckData=True
Encroach Param=-1 ,0,0, 0
Flow Ratio Tolerance=0.1
Flow Ratio Min Ratio=0.5
Flow Ratio Max Ratio=4
Flow Ratio Max Iterations= 10
Computation Interval=1MIN
Output Interval=1HOUR
Instantaneous Interval=1HOUR
Mapping Interval=1HOUR
Computation Time Step Use Courant=        0
Computation Time Step Use Time Series=    0
Computation Time Step Count To Double=0
Computation Time Step Max Doubling=0
Computation Time Step Max Halving=0
Computation Time Step Residence Courant=0
Run HTab= 0
Run UNet= 0
Run Sediment= 0
Run PostProcess= 0
Run WQNet= 0
Run RASMapper= 0
UNET Theta= 1
UNET Theta Warmup= 1
UNET ZTol= 0.02
UNET ZSATol= 0.02
UNET MxIter= 20
UNET Max Iter WO Improvement= 0
UNET MaxInSteps= 0
UNET DtIC= 0
UNET DtMin= 0
UNET MaxCRTS= 20
UNET WFStab= 2
UNET SFStab= 1
UNET WFX= 1
UNET SFX= 1
UNET Gravity=32.17405
UNET 1D Methodology=Finite Difference
UNET DSS MLevel= 4
UNET Pardiso=0
UNET DZMax Abort= 100
UNET Use Existing IB Tables=-1
UNET Froude Reduction=False
UNET Froude Limit= 0.8
UNET Froude Power= 4
UNET D1 Cores= 0
UNET WindReference=Eulerian
UNET WindDragFormulation=Hsu (1988)
UNET D2 Coriolis=0
UNET D2 Cores= 0
UNET D2 Theta= 1
UNET D2 Theta Warmup= 1
UNET D2 Z Tol= 0.01
UNET D2 Volume Tol= 0.01
UNET D2 Max Iterations= 20
UNET D2 Equation= 0
UNET D2 RampUpFraction=0.1
UNET D2 TimeSlices= 1
UNET D2 Turbulence Formulation=None
UNET D2 Eddy Viscosity=0.3
UNET D2 Transverse Eddy Viscosity=0.1
UNET D2 Smagorinsky Mixing=0.05
UNET D2 BCVolumeCheck=0
UNET D2 Cores=0
UNET D2 SolverType=PARDISO (Direct)
UNET D2 Minimum Iterations= 3
UNET D2 Maximum Iterations= 30
UNET D2 Restart Number= 10
UNET D2 Relaxation Coeff=1.3
UNET D2 SOR Precondition Iterations= 10
UNET D2 ILUT Maximum Fill= 8
UNET D2 ILUT Tolerance=1E-08
UNET D2 Convergence Tolerance=0.00001
PS Theta= 1
PS WS Tol= 0.01
PS Volume Tol= 0.01
PS Max Iterations= 20
PS Time Slices= 1
PS Iterate With 2D=0
PS Cores=0
UNET D1D2 MaxIter= 0
UNET D1D2 ZTol=0.01
UNET D1D2 QTol=0.1
UNET D1D2 MinQTol=1
Write IC File= 0
Write IC File at Fixed DateTime=0
Write IC File at Sim End=0
Echo Input=False
Echo Parameters=False
Echo Output=False
Write Detailed= 0
HDF Write Warmup=0
HDF Write Time Slices=0
HDF Flush=0
HDF Compression= 1
HDF Chunk Size= 1
HDF Spatial Parts= 1
HDF Use Max Rows=0
HDF Fixed Rows= 1
Calibration Method= 0
Calibration Iterations= 20
Calibration Max Change=0.05
Calibration Tolerance=0.2
Calibration Maximum=1.5
Calibration Minimum=0.5
Calibration Optimization Method= 1
WQ AD Non Conservative
WQ ULTIMATE=-1
WQ Max Comp Step=1HOUR
WQ Output Interval=15MIN
WQ Output Selected Increments= 0
WQ Create Restart=0
WQ Fixed Restart=0
WQ System Summary=0
WQ Write To DSS=0
Sorting and Armoring Iterations= 10
XS Update Threshold= 0.02
Bed Roughness Predictor= 0
Hydraulics Update Threshold= 0.02
Energy Slope Method= 1
Volume Change Method= 1
Sediment Retention Method= 0
Sediment TS Multiplier= 1
Warm Up Method= 0
XS Weighting Method= 0
Number of US Weighted Cross Sections= 1
Number of DS Weighted Cross Sections= 1
Upstream XS Weight=0
Main XS Weight=1
Downstream XS Weight=0
Number of DS XS's Weighted with US Boundary= 1
Upstream Boundary Weight= 1
Weight of XSs Associated with US Boundary= 0
Number of US XS's Weighted with DS Boundary= 1
Downstream Boundary Weight= 0.5
Weight of XSs Associated with DS Boundary= 0.5
Percentile Method= 0
Sediment Output Level= 3
Mass or Volume Output= 0
Output Increment Type= 1
Profile and TS Output Increment= 1
Transport Output Increment 1
XS Output Flag= 0
XS Output Increment= 10
Read HDF5 Sediment Hotstart= 0
Sediment Hotstart Type= 0
Write Gradation File= 0
Read Gradation Hotstart= 0
Write HDF5 File= 1
Write Binary Output= 1
Write DSS Sediment File= 0
DSS Sediment Output Type= 1
SV Curve= 0
Specific Gage Flag= 0
Subcell Erosion Methods= 0
Subcell Deposition Methods= 0
Advection Scheme= 1
Matrix Solver= 0
Implicit Weighting Factor= 1
Maximum Outer Loop Convergence Iterations= 5
Convergence Maximum Absolute= 0.001
Convergence RMSE= 0.0001
Grain Fractions Max Abs Error= 0.001
Max Subgrid Regions= 1
Max Subgrid Length Scale= 3.402823E+38
Initial Layer Thickness= 3
Min Layer Thickness= 0.1
Max Layer Thickness= 6
Number of Layers= 5

--- NorthArroyodeDom.f12 (steady flow) ---

Flow Title=NDB Flow
Program Version=6.50
Number of Profiles= 1
Profile Names=PF 1
River Rch & RM=NDB,1               ,2799
     658
Boundary for River Rch & Prof#=NDB,1               , 1
Up Type= 3
Up Slope=0.025
Dn Type= 1
Dn Known WS=5320
DSS Import GetInterval= 0
DSS Import GetPeak= 0
DSS Import FillOption= 0

--- NorthArroyodeDom.g02 (geometry) ---

Geom Title=NORTH DOMINGO BACA
Program Version=6.50

River Reach=NDB             ,1
Reach XY= 6
1.043191824232410.564593222737080.983946760438180.56464342114635
0.796761330784630.571078239114550.188791354713350.89857139955828
-0.66885162486450.89695014628876-0.72883799586450.89695000345818

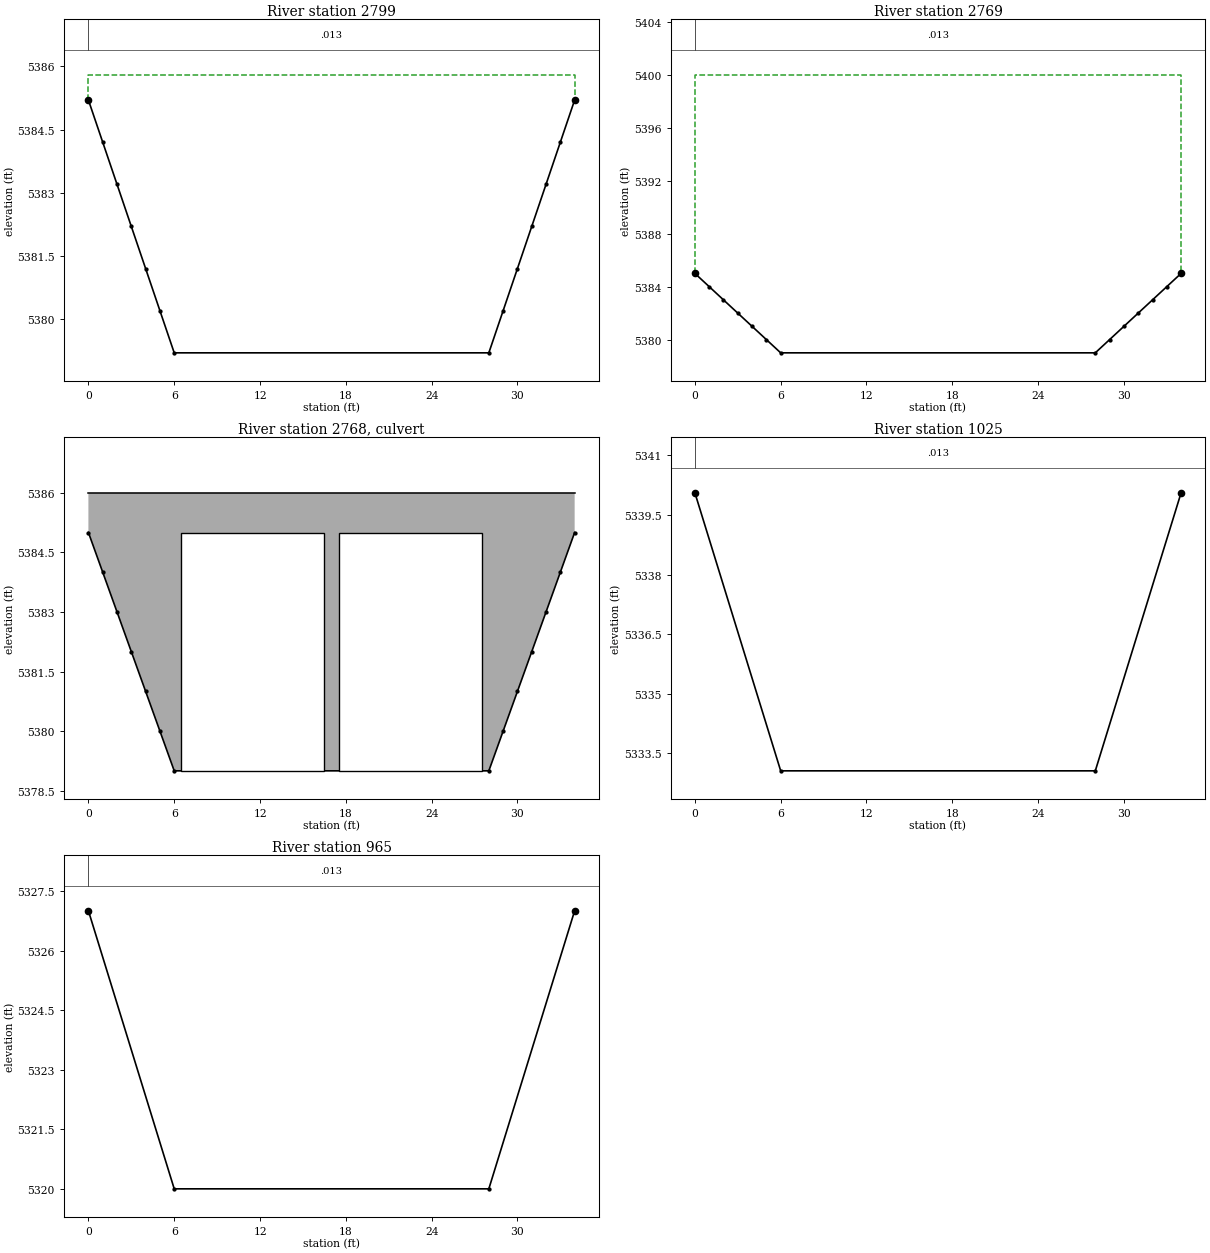
Type RM Length L Ch R = 1 ,2799    ,30,30,30
XS GIS Cut Line= 2
1.043192011366460.520819367972141.043192011366460.62457959268312
#Sta/Elev= 14
       0  5385.2       1  5384.2       2  5383.2       3  5382.2       4  5381.2
       5  5380.2       6  5379.2      28  5379.2      29  5380.2      30  5381.2
      31  5382.2      32  5383.2      33  5384.2      34  5385.2
#Mann= 1 ,-1,0
       0    .013       0
#XS Ineff= 2 , 0
             -10  5385.8      44          5385.8
Permanent Ineff=
       T       T
Bank Sta=0,34
XS Rating Curve= 0 ,0
Exp/Cntr(USF)=0,0
Exp/Cntr=0.3,0.1

Type RM Length L Ch R = 1 ,2769    ,1743,1743,1743
XS GIS Cut Line= 2
0.986053288403550.501433000261030.981587354803990.63177773270865
#Sta/Elev= 14
       0    5385       1    5384       2    5383       3    5382       4    5381
       5    5380       6    5379      28    5379      29    5380      30    5381
      31    5382      32    5383      33    5384      34    5385
#Mann= 1 ,-1,0
       0    .013       0
#XS Ineff= 2 , 0
             -10    5400      44            5400
Permanent Ineff=
       T       T
Bank Sta=0,34
XS Rating Curve= 0 ,0
Exp/Cntr(USF)=0,0
Exp/Cntr=0.3,0.1

Type RM Length L Ch R = 2 ,2768    ,,,
Bridge Culvert--1,0,-1,-1, 0
Deck Dist Width WeirC Skew NumUp NumDn MinLoCord MaxHiCord MaxSubmerge Is_Ogee
1,34,2.6,0, 4, 4, , , 0.98, 0, 0,0,,
       0       6      28      34
    5386    5386    5386    5386
    5385    5379    5379    5385
       0       6      28      34
    5342    5342    5342    5342
 5340.06 5333.06 5333.06 5340.06
BR Coef=-1 , 0 , 0 ,, 0 ,,,0.8,-1,,0,
WSPro=,,,, 1 ,,,, 0 ,,,, 0 ,,,,-1 ,-1 ,-1 , 0 , 0 , 0 , 0 , 0
Multiple Barrel Culv=2,6,10,1742,0.013,0.3,1,8,1,5379,5333.06, 2,Culvert #1  , 0 ,1
    11.5    11.5    22.5    22.5
BC Culvert Barrel=1,Barrel # 2,0
BC Culvert Barrel=2,Barrel # 1,0
Culvert Bottom n=0.013
BC Design=,, 0 ,, 0 ,,,,,,
BC Use User HTab Curves=0
BC User HTab FreeFlow(D)= 0

Type RM Length L Ch R = 1 ,1025    ,60,60,60
XS GIS Cut Line= 2
-0.66885162486450.86290382762877-0.66885162486450.94072398456589
#Sta/Elev= 4
       0 5340.06       6 5333.06      28 5333.06      34 5340.06
#Mann= 1 ,-1,0
       0    .013       0
#XS Ineff= 2 , 0
             -10    5325      44            5325
Permanent Ineff=
       T       T
Bank Sta=0,34
XS Rating Curve= 0 ,0
Exp/Cntr(USF)=0,0
Exp/Cntr=0.3,0.1

Type RM Length L Ch R = 1 ,965     ,0,0,0
XS GIS Cut Line= 2
-0.72883799583690.85966132108972-0.72883799583690.94234523783541
#Sta/Elev= 4
       0    5327       6    5320      28    5320      34    5327
#Mann= 1 ,-1,0
       0    .013       0
Bank Sta=0,34
XS Rating Curve= 0 ,0
Exp/Cntr(USF)=0,0
Exp/Cntr=0.3,0.1
LCMann Table=0

Chan Stop Cuts=-1
Use User Specified Reach Order=0
Composite Channel Slope=5